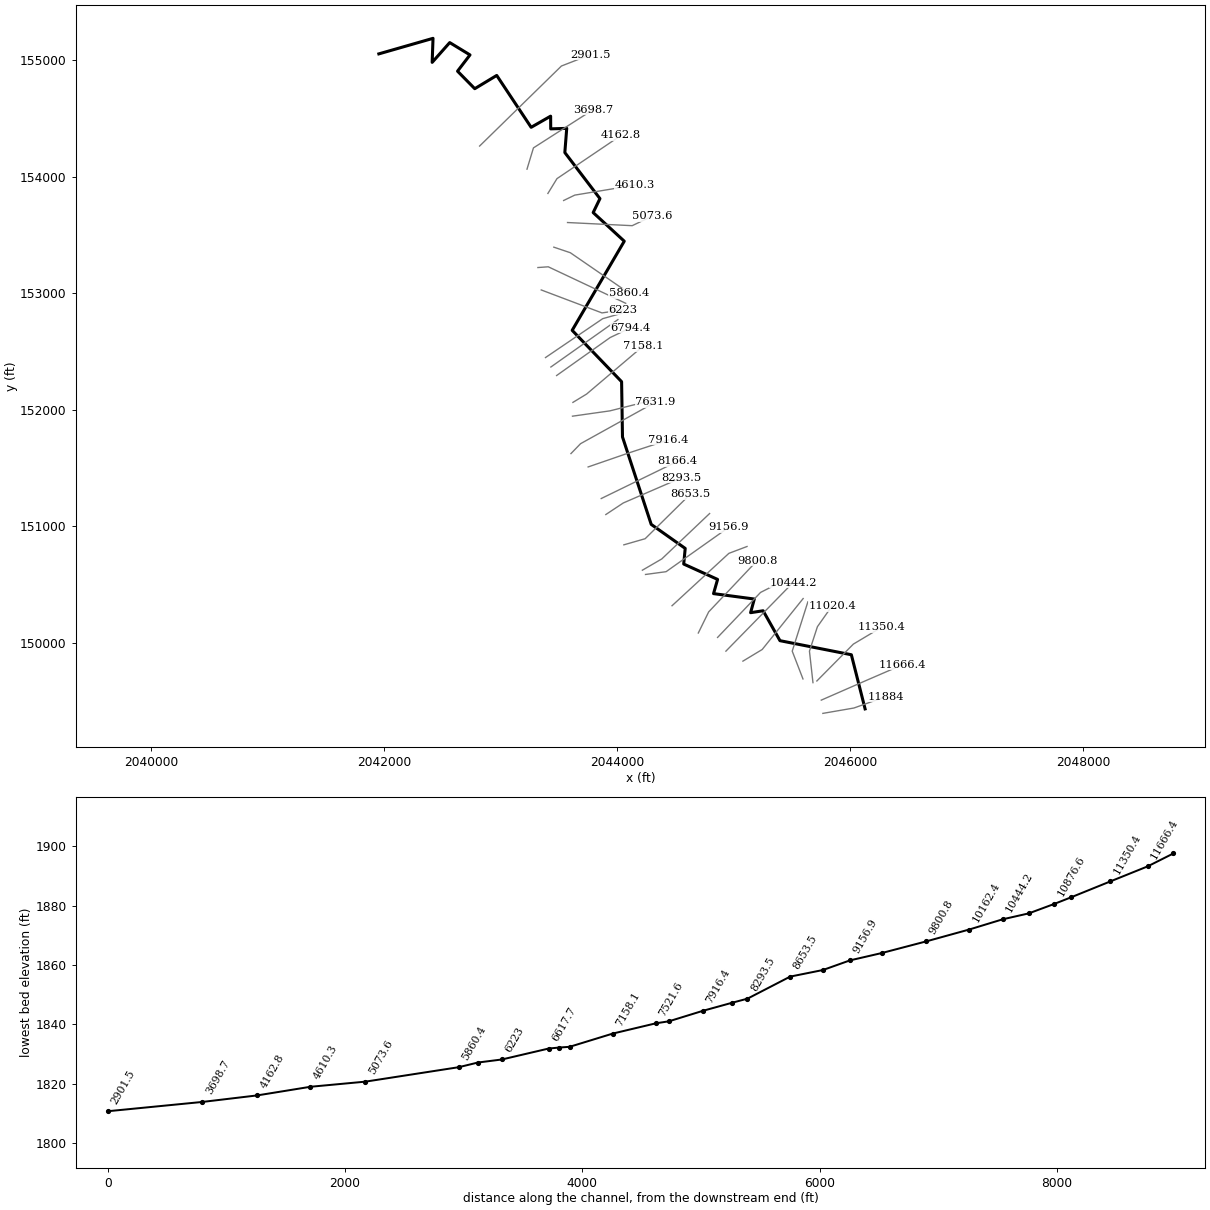
--- CRCKDCK.prj (project) ---

Proj Title=CRCKDCK
Current Plan=p01
Default Exp/Contr=0,0
English Units
Geom File=g01
Flow File=f01
Plan File=p01
BEGIN DESCRIPTION:
END DESCRIPTION:
DSS Export Rating Curves= 0
DSS Export Rating Curve Sorted= 0
DSS Export Volume Flow Curves= 0
DXF OffsetX= 0
DXF OffsetY= 0
DXF ScaleX= 0
DXF ScaleY= 0

--- CRCKDCK.p01 (plan) ---

Plan Title=Floodplain
Program Version=4.00
Geom File=g01
Flow File=f01
K Sum by GR=0
Std Step Tol=0.01
Critical Tol=0.01
Num of Std Step Trials=20
Max Error Tol=0.3
Flow Tol Ratio=0.001
Split Flow NTrial=30
Split Flow Tol=0.02
Split Flow Ratio=0.02
Log Output Level=0
Friction Slope Method=1
Unsteady Friction Slope Method=2
Unsteady Bridges Friction Slope Method=1
Global Log Level=0
CheckData=False
Run HTab=0
Run UNet=0
Run PostProcess=0
UNET Theta=0
UNET Theta Warmup=0
UNET ZTol=0
UNET ZSATol=0
UNET MxIter=0
UNET MaxInSteps=0
UNET DtIC=0
UNET DtMin=0
UNET MaxCRTS=0
UNET WFStab=0
UNET SFStab=0
UNET WFX=0
UNET SFX=0
UNET DSS MLevel=0
UNET DZMax Abort=0
UNET Convert EG Bridges=0
UNET Use Existing IB Tables=0
UNET Froude Limit=0
UNET Froude Power=0
Write IC File=0
Echo Input=False
Echo Output=False
Write Detailed=0

--- CRCKDCK.f01 (steady flow) ---

Flow Title=NFF Regression Equation
Program Version=4.10
Number of Profiles= 1
Profile Names=P100yr
River Rch & RM=CRCKDCK,Main            ,11884
437.0178
River Rch & RM=CRCKDCK,Main            ,11666.4
747.0507
River Rch & RM=CRCKDCK,Main            ,10664.6
754.0132
River Rch & RM=CRCKDCK,Main            ,10444.2
946.1421
River Rch & RM=CRCKDCK,Main            ,7631.9
974.8054
River Rch & RM=CRCKDCK,Main            ,5860.4
1081.409
River Rch & RM=CRCKDCK,Main            ,5073.6
1188.156
River Rch & RM=CRCKDCK,Main            ,441
1226.989
River Rch & RM=CRCKDCK,Main            ,148.2
1229.678
Boundary for River Rch & Prof#=CRCKDCK,Main            , 1
Up Type= 0
Dn Type= 3
Dn Slope=0.004776
DSS Import GetInterval= 0
DSS Import GetPeak= 0
DSS Import FillOption= 0

--- CRCKDCK.g01 (geometry) ---

Geom Title=USGS 10m DEM
Program Version=4.10

River Reach=CRCKDCK         ,Main
Reach XY= 30
     2046127.949      149433.304     2046009.946      149898.204
     2045397.156      150019.037     2045252.538      150275.808
     2045144.986      150259.315     2045176.844      150376.502
     2044826.844      150422.943     2044861.566      150544.905
     2044570.768       150676.85     2044583.572      150811.181
     2044291.688      151017.388      2044045.16      151768.082
     2044037.521      152242.388     2043613.216       152683.36
      2044060.38       153448.58     2043793.453       153694.24
     2043851.613       153814.06     2043550.154      154209.547
     2043566.474      154417.185     2043428.974      154413.019
     2043428.279      154522.046     2043260.918      154426.213
     2042965.432      154871.699      2042776.89       154757.81
     2042628.974      154908.157     2042735.918      155047.741
      2042561.96      155153.644     2042411.265      154983.852
     2042418.557      155190.102      2041953.43      155056.663

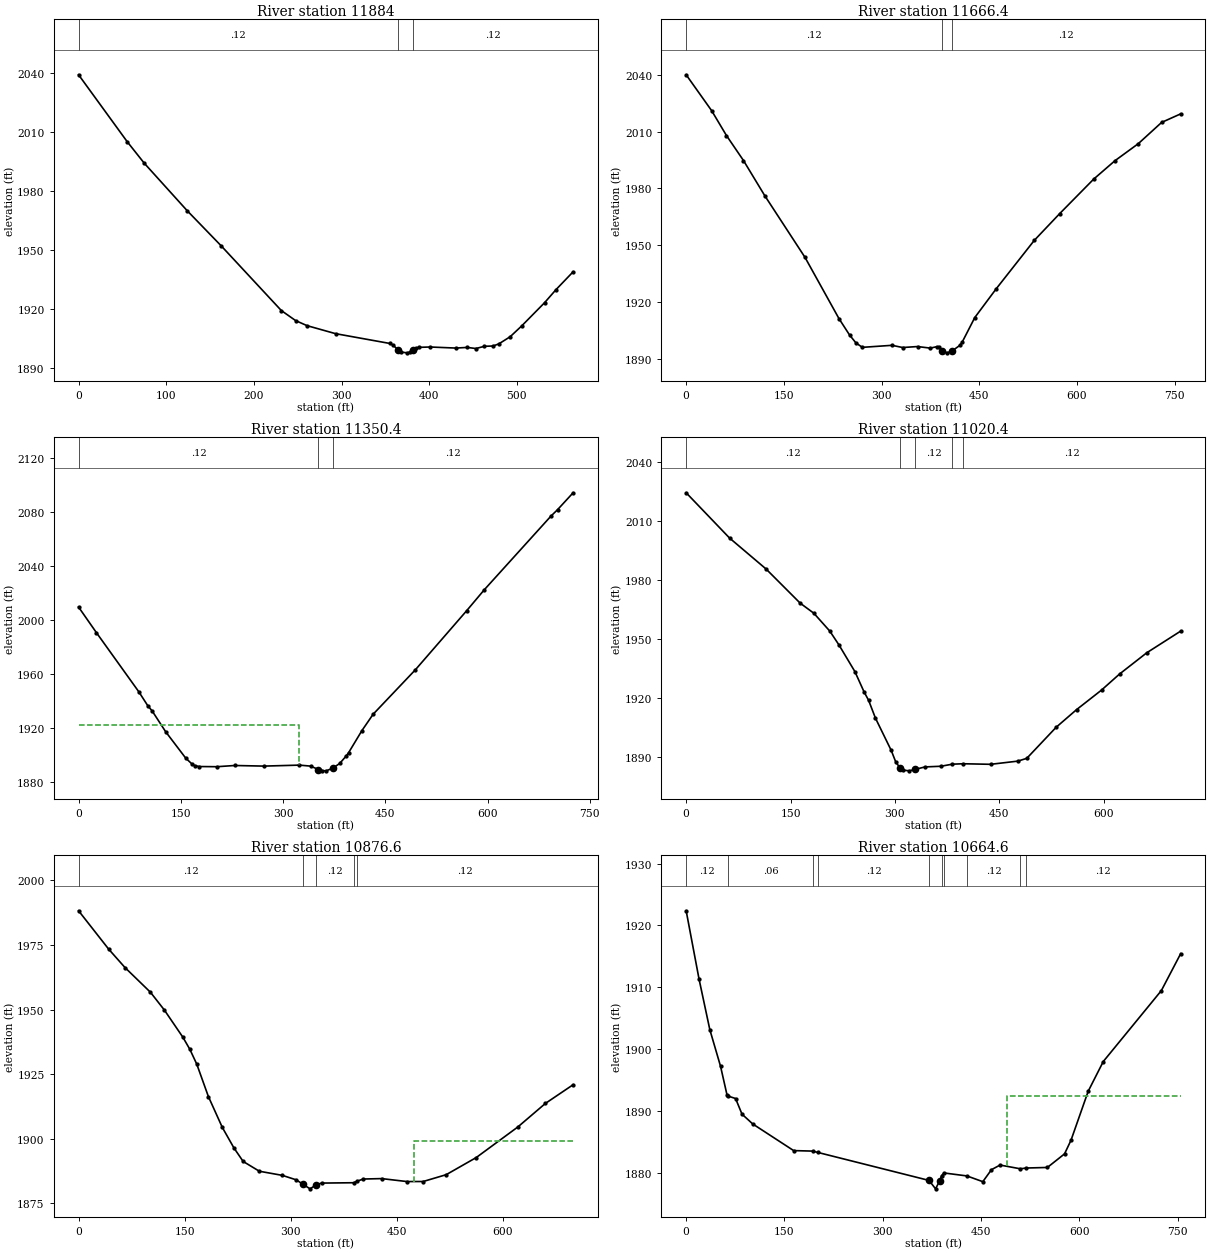
Type RM Length L Ch R = 1 ,11884   ,212.1,217.5,220.2
XS GIS Cut Line= 3
     2045765.421      149394.839     2046031.862      149440.864
     2046308.557      149539.456
#Sta/Elev= 30
       0    2039    55.4    2005    74.9 1994.03   123.8  1969.9   162.9 1951.88
   231.3 1919.06   247.6 1913.96   260.6 1911.39   293.2 1907.31   355.2 1902.32
   358.5 1901.54   364.2 1899.18   368.3 1897.92   374.8 1897.56   378.1 1897.93
   381.4 1898.85   384.6 1899.92   387.9 1900.35   400.9 1900.53   430.3 1899.99
   443.4 1900.31   453.2 1899.76     463 1900.89   472.7 1901.04   479.3  1902.1
   492.3 1905.75   505.4 1911.23   531.5 1923.04   544.5 1929.67   564.1 1938.78
#Mann= 3 ,-1 , 0
       0     .12       0   364.2    .045       0   381.4     .12       0
Bank Sta=364.2,381.4
XS Rating Curve= 0 ,0
Exp/Cntr=0.3,0.1

Type RM Length L Ch R = 1 ,11666.4 ,306,316,323.8
XS GIS Cut Line= 3
     2045751.692       149508.56     2046118.904      149669.291
     2046447.905      149811.679
#Sta/Elev= 30
       0 2039.97    39.1 2021.04    61.9 2007.89      88 1994.71   120.6  1976.2
   182.5 1943.57   234.6 1911.28   250.9  1902.6   260.7 1898.42   270.5 1896.09
   316.1 1897.16   332.4    1896   355.2 1896.51   374.8 1895.69   384.6 1896.42
   387.8  1896.2   393.3 1894.22   400.8 1893.19   408.3 1894.18   420.4 1897.18
   423.7 1898.77   443.2 1911.84   475.8 1926.89   534.5 1952.55   573.6 1966.71
   625.7 1984.89   658.3 1994.59   694.2  2003.6     730 2014.82   759.3 2019.34
#Mann= 3 ,-1 , 0
       0     .12       0   393.3    .045       0   408.3     .12       0
Bank Sta=393.3,408.3
XS Rating Curve= 0 ,0
Exp/Cntr=0.3,0.1

Type RM Length L Ch R = 1 ,11350.4 ,317.8,330,339.1
XS GIS Cut Line= 3
     2045713.822      149673.033     2046027.091      149989.484
     2046267.765      150133.235
#Sta/Elev= 30
       0 2009.48    26.2  1990.5    88.4 1946.68   101.5 1936.39     108 1932.46
   127.7 1917.14   157.2 1897.52     167 1892.88   170.3 1891.99   176.8 1891.29
     203 1891.16   229.2 1892.06   271.8 1891.61   324.1 1892.34   340.5  1891.6
   351.9 1889.08   356.9 1888.26   363.4  1888.1   373.2 1890.16   383.1 1893.55
   392.9 1899.25   396.2 1901.56   415.8 1917.98   432.2 1930.06   494.2 1963.02
   569.2 2006.66   595.2 2022.26     693 2076.85   702.8 2081.68   725.6 2094.19
#Mann= 3 ,-1 , 0
       0     .12       0   351.9    .045       0   373.2     .12       0
#XS Ineff= 2 , 0
           323.8 1922.32
Permanent Ineff=
       F       F
Bank Sta=351.9,373.2
XS Rating Curve= 0 ,0
Exp/Cntr=0.3,0.1

Type RM Length L Ch R = 1 ,11020.4 ,143.4,143.8,143.8
XS GIS Cut Line= 4
     2045680.428      149658.722     2045650.214      149929.056
     2045718.592      150138.962     2045844.218      150317.065
#Sta/Elev= 30
       0 2024.54    62.3 2001.48   114.7 1985.72   163.9 1968.25   183.5 1963.12
   206.5 1953.98   219.6 1946.95   242.5 1933.36   255.6 1923.07   262.2 1918.72
     272 1909.66   294.7 1893.17   301.2  1887.3   307.7 1884.09     311 1883.16
   320.7 1882.76   328.6 1883.48   343.4 1884.76   366.2  1885.1  382.461886.154
  397.881886.375   437.6 1886.09   476.6 1887.71   489.5 1889.13   531.8    1905
   561.1 1913.98   596.9 1923.93   622.9 1932.14   661.9 1942.95   710.7 1954.01
#Mann= 5 ,-1 , 0
       0     .12       0   307.7    .045       0   328.6     .12       0
  382.46     .06       0  397.88     .12       0
Bank Sta=307.7,328.6
XS Rating Curve= 0 ,0
Exp/Cntr=0.3,0.1

Type RM Length L Ch R = 1 ,10876.6 ,220.4,212,201.8
XS GIS Cut Line= 3
     2045594.557      149690.526     2045502.325      149929.056
     2045636.603      150352.025
#Sta/Elev= 30
       0 1988.26    42.6 1973.38    65.6 1966.27   101.6  1956.7   121.3 1949.81
   147.5 1939.27   157.4 1934.56   167.2 1928.81   183.6 1916.27   203.3 1904.31
   219.7 1896.37   232.8 1891.11   255.7 1887.32   288.4 1885.71     308 1883.97
   317.7  1882.2   327.5  1880.5   336.3 1882.11   343.8 1882.73  389.171882.866
  393.281883.396   402.6  1884.3   428.7 1884.47   464.6 1883.32   487.4 1883.34
     520 1885.99   562.5 1892.63   621.2 1904.45   660.4 1913.62   699.5 1920.85
#Mann= 5 ,-1 , 0
       0     .12       0   317.7    .045       0   336.3     .12       0
  389.17     .06       0  393.28     .12       0
#XS Ineff= 2 , 0
                          474.45         1898.86
Permanent Ineff=
       F       F
Bank Sta=317.7,336.3
XS Rating Curve= 0 ,0
Exp/Cntr=0.3,0.1

Type RM Length L Ch R = 1 ,10664.6 ,207.2,220.4,227.9
XS GIS Cut Line= 3
      2045079.11      149843.359     2045244.712      149943.368
     2045596.147      150380.673
#Sta/Elev= 30
       0 1922.37    19.7 1911.29    36.1 1903.13    52.5 1897.18    62.3 1892.57
   64.511892.356    75.4 1891.98    85.2 1889.45   101.6 1887.86     164 1883.55
  192.821883.469  201.191883.245   370.6 1878.72   380.5 1877.36     387  1878.7
   389.7 1879.49  393.381879.931  428.351879.449   452.6 1878.52   465.8 1880.46
   478.9 1881.21  509.941880.603  518.631880.729   551.1 1880.82   577.3 1883.02
   587.2 1885.24   613.4 1893.16   636.4 1897.97     725 1909.45   754.5 1915.43
#Mann= 10 ,-1 , 0
       0     .12       0   64.51     .06       0  192.82     .08       0
  201.19     .12       0   370.6    .045       0   389.7     .12       0
  393.38     .06       0  428.35     .12       0  509.94     .06       0
  518.63     .12       0
#XS Ineff= 2 , 0
                          489.77         1892.36
Permanent Ineff=
       F       F
Bank Sta=370.6,387
XS Rating Curve= 0 ,0
Exp/Cntr=0.3,0.1

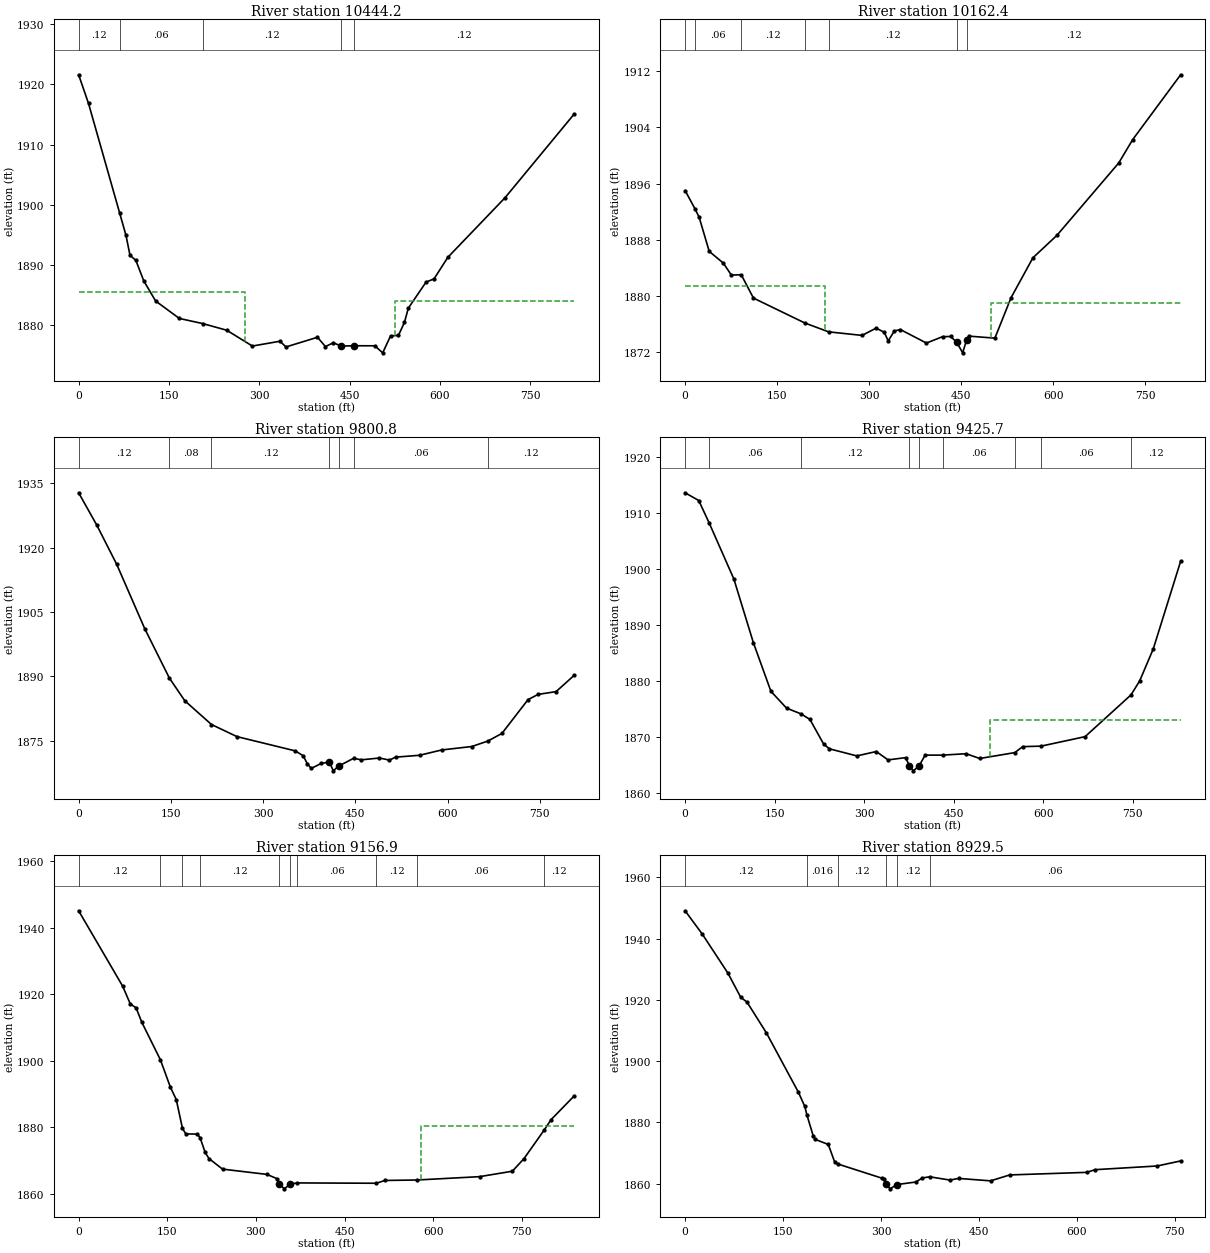
Type RM Length L Ch R = 1 ,10444.2 ,262.8,281.9,267
XS GIS Cut Line= 2
     2044933.033      149929.056     2045508.906      150517.303
#Sta/Elev= 30
       0  1921.6    16.4 1916.84   67.951898.682    78.7 1894.88    85.3 1891.59
    95.1 1890.73   108.2 1887.33   127.9 1883.98   167.3 1881.08  206.191880.226
     246 1879.12   288.6 1876.49   334.5 1877.29   344.4 1876.34   396.8 1877.95
     410  1876.4   423.1 1877.04   436.2 1876.48   457.4 1876.54     492 1876.53
   505.1 1875.36   518.2 1878.18   531.3 1878.26   541.2 1880.41   547.7 1882.79
   577.2 1887.13   590.4 1887.66   613.3 1891.24   708.4 1901.16   823.2 1915.07
#Mann= 5 ,-1 , 0
       0     .12       0   67.95     .06       0  206.19     .12       0
   436.2    .045       0   457.4     .12       0
#XS Ineff= 2 , 0
          276.99 1885.43  526.29            1884
Permanent Ineff=
       F       F
Bank Sta=436.2,457.4
XS Rating Curve= 0 ,0
Exp/Cntr=0.3,0.1

Type RM Length L Ch R = 1 ,10162.4 ,331.2,361.6,355.8
XS GIS Cut Line= 3
     2044861.474      150046.731       2045230.4       150433.15
     2045473.965      150557.061
#Sta/Elev= 30
       0 1895.02   16.281892.388    22.9 1891.22    39.3 1886.36    62.3 1884.69
    75.4 1882.98   91.461883.038   111.4 1879.71  195.121876.167  233.831874.909
   288.4  1874.4   311.4 1875.44   324.5 1874.84     331 1873.62   340.9 1875.02
   350.7 1875.24   393.3 1873.31   419.5 1874.22   432.6 1874.25   442.5 1873.44
   452.3 1871.92   458.9  1873.8   462.2  1874.3   504.8 1874.01     531 1879.74
   566.8 1885.45   605.8 1888.63   706.7 1898.95   729.4 1902.27   807.5 1911.49
#Mann= 7 ,-1 , 0
       0     .12       0   16.28     .06       0   91.46     .12       0
  195.12     .06       0  233.83     .12       0   442.5    .045       0
   458.9     .12       0
#XS Ineff= 2 , 0
          228.38 1881.43  499.15         1879.05
Permanent Ineff=
       F       F
Bank Sta=442.5,458.9
XS Rating Curve= 0 ,0
Exp/Cntr=0.3,0.1

Type RM Length L Ch R = 1 ,9800.8  ,374.6,375.2,350.6
XS GIS Cut Line= 3
     2044696.093      150084.896     2044785.144      150266.179
     2045200.187      150705.074
#Sta/Elev= 30
       0 1932.76    29.3 1925.28    61.9 1916.09   107.5 1901.08  147.551889.572
   172.7 1884.27  216.061878.734   257.5 1875.91   352.2 1872.59   365.2 1871.46
   371.8 1869.62   378.3 1868.49   394.6 1869.66   407.9 1869.99   414.2 1867.93
   422.9 1869.04  447.231870.848   459.9  1870.5   489.3 1870.92   505.6 1870.43
   515.4 1871.12   554.6 1871.56   590.5  1872.8   639.5  1873.6  665.431874.864
   688.5 1876.65   730.9 1884.53   747.3 1885.75   776.6  1886.4     806  1890.2
#Mann= 7 ,-1 , 0
       0     .12       0  147.55     .08       0  216.06     .12       0
   407.9    .045       0   422.9     .12       0  447.23     .06       0
  665.43     .12       0
Bank Sta=407.9,422.9
XS Rating Curve= 0 ,0
Exp/Cntr=0.3,0.1

Type RM Length L Ch R = 1 ,9425.7  ,269.4,268.8,265.6
XS GIS Cut Line= 3
     2044470.523      150318.984     2044958.476      150768.682
     2045114.316       150827.52
#Sta/Elev= 30
       0 1913.54    22.9 1912.16   40.391908.146    81.7 1898.18   114.4 1886.83
   143.8 1878.16     170 1875.17  194.511874.134   209.2 1873.15   232.1 1868.77
   241.9 1867.92   287.7 1866.66   320.3 1867.44     340 1865.95   369.4 1866.35
   375.9 1864.91   382.4    1864   392.2 1864.91   402.1  1866.8  431.511866.801
   470.7 1867.05   493.6  1866.2  552.381867.248   565.5 1868.31  596.431868.402
   670.1 1870.09  747.011877.526   761.6 1880.03   784.4 1885.74   830.2 1901.34
#Mann= 9 ,-1 , 0
       0    .016       0   40.39     .06       0  194.51     .12       0
   375.9    .045       0   392.2     .12       0  431.51     .06       0
  552.38     .12       0  596.43     .06       0  747.01     .12       0
#XS Ineff= 2 , 0
                          510.46         1873.07
Permanent Ineff=
       F       F
Bank Sta=375.9,392.2
XS Rating Curve= 0 ,0
Exp/Cntr=0.3,0.1

Type RM Length L Ch R = 1 ,9156.9  ,206.7,227.3,224.3
XS GIS Cut Line= 3
     2044242.885      150587.399     2044419.398      150611.252
     2044958.476      150992.901
#Sta/Elev= 30
       0 1945.12    74.5 1922.46    87.4 1917.12    97.2 1915.94   106.9 1911.61
  138.381900.315   155.4 1892.03   165.2 1888.38  175.721879.684   181.4 1878.03
     201 1877.98  205.631876.862   214.1 1872.46   220.6 1870.62   243.5 1867.45
   318.7 1865.86   335.1 1864.62  339.74 1862.98   348.2 1861.52   358.1 1862.97
  370.191863.298  503.921863.201   518.2 1864.04  572.131864.175   678.4 1865.18
     734 1866.82   753.6 1870.59   788.11879.251   799.4  1882.3   838.6 1889.45
#Mann= 10 ,-1 , 0
       0     .12       0  138.38     .06       0  175.72    .016       0
  205.63     .12       0  339.74    .045       0   358.1     .12       0
  370.19     .06       0  503.92     .12       0  572.13     .06       0
   788.1     .12       0
#XS Ineff= 2 , 0
                          579.99         1880.48
Permanent Ineff=
       F       F
Bank Sta=339.74,358.1
XS Rating Curve= 0 ,0
Exp/Cntr=0.3,0.1

Type RM Length L Ch R = 1 ,8929.5  ,302.7,276.1,267.9
XS GIS Cut Line= 3
     2044215.852      150623.974     2044382.823      150720.976
     2044793.095      151110.576
#Sta/Elev= 30
       0 1949.05    26.2 1941.48    65.5 1928.72    85.1 1920.84    94.9 1919.21
   124.4 1909.23   173.5 1889.83   183.3 1885.18  186.421882.485   196.4 1875.43
   199.6  1874.4   219.3 1872.76   229.1 1867.03  233.871866.386     301 1861.79
   304.3 1861.37   307.6 1859.86   314.1 1858.28   324.2 1859.67   353.4 1860.51
   363.2 1861.83  374.641862.209   405.7 1861.14   418.8 1861.68   467.8 1860.89
   497.2 1862.82     615 1863.66   628.1 1864.54   722.9 1865.74   758.9 1867.39
#Mann= 6 ,-1 , 0
       0     .12       0  186.42    .016       0  233.87     .12       0
   307.6    .045       0   324.2     .12       0  374.64     .06       0
Bank Sta=307.6,324.2
XS Rating Curve= 0 ,0
Exp/Cntr=0.3,0.1

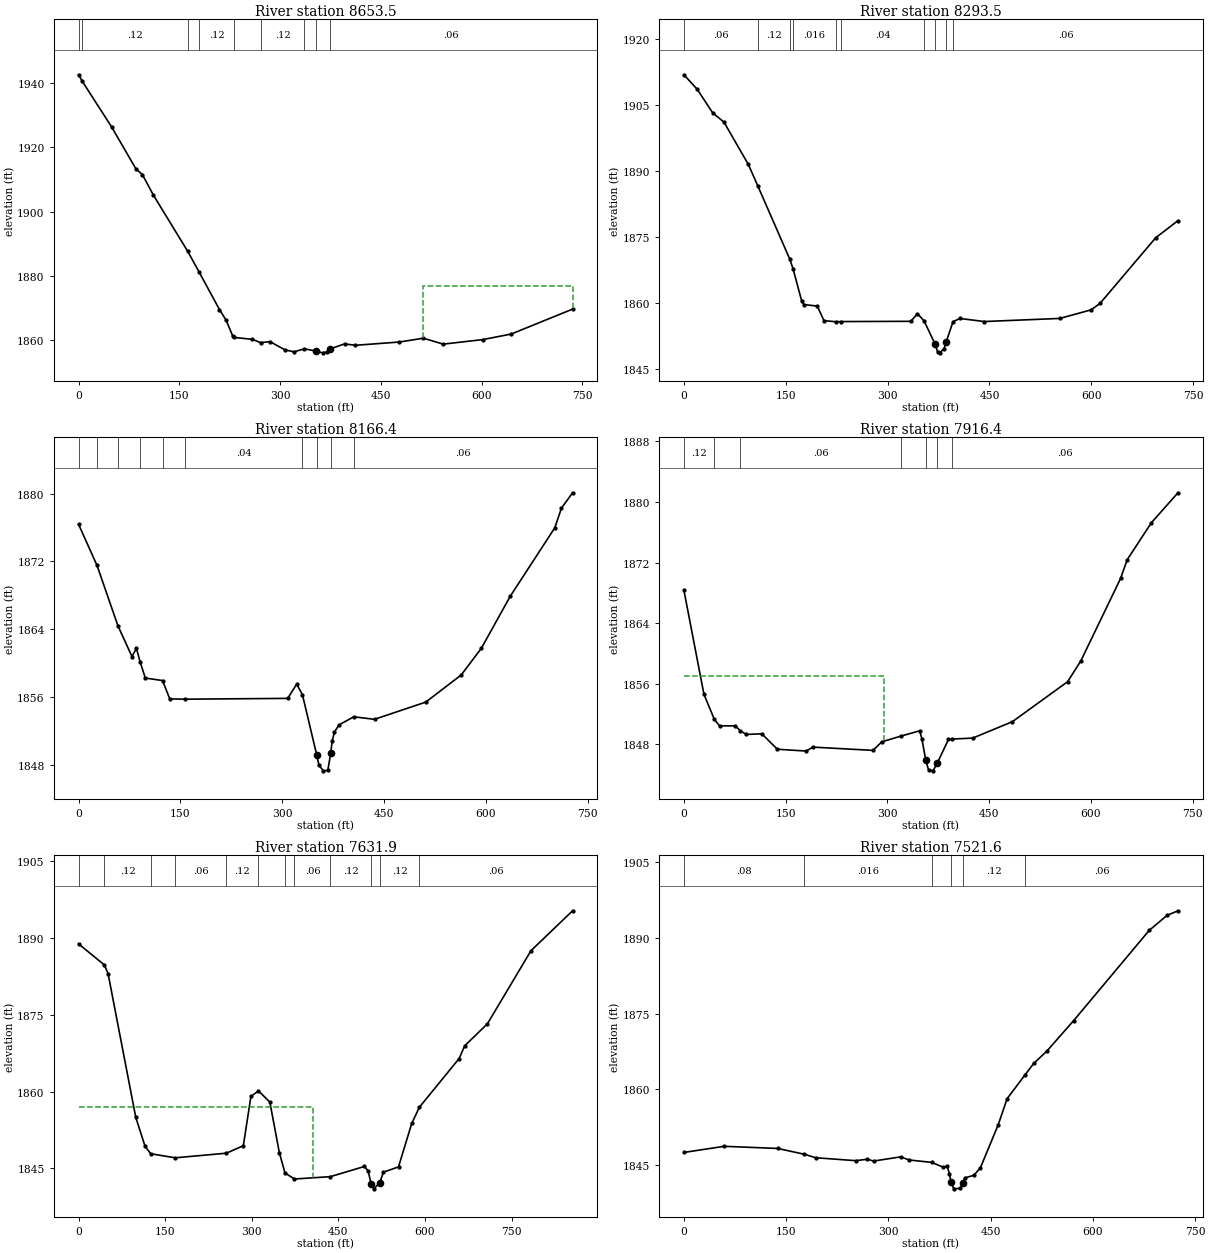
Type RM Length L Ch R = 1 ,8653.5  ,340.8,360,348.2
XS GIS Cut Line= 3
     2044056.832      150841.832     2044239.705      150894.308
     2044627.816      151277.083
#Sta/Elev= 30
       0 1942.51    5.621940.453    49.2  1926.3    85.3 1913.29    95.1 1911.46
   111.5 1905.06  162.531887.607  179.511881.168   209.8  1869.5   219.6 1866.24
   229.4 1861.32  231.39 1860.85   258.8 1860.26     2711859.227   284.9 1859.54
   307.8 1856.94   320.8 1856.39  336.211857.306   353.5 1856.61   363.2 1856.06
   369.8 1856.38     374 1857.24   395.9 1858.84   412.2 1858.41   477.5 1859.42
   513.4 1860.61   542.8 1858.77   601.5 1860.17     644  1861.9   735.4 1869.65
#Mann= 9 ,-1 , 0
       0     .06       0    5.62     .12       0  162.53     .06       0
  179.51     .12       0  231.39    .016       0     271     .12       0
  336.21     .06       0   353.5    .045       0     374     .06       0
#XS Ineff= 2 , 0
                          513.28         1876.86
Permanent Ineff=
       F       F
Bank Sta=353.5,374
XS Rating Curve= 0 ,0
Exp/Cntr=0.3,0.1

Type RM Length L Ch R = 1 ,8293.5  ,125.9,127.1,127.9
XS GIS Cut Line= 3
     2043902.039      151101.795     2044052.061      151201.217
     2044554.565      151419.075
#Sta/Elev= 30
       0 1911.88    19.6 1908.57    42.5 1903.19    58.9 1901.13    94.9 1891.48
  108.941886.557  155.78 1869.99  160.711867.751   173.4 1860.45   176.7 1859.61
   196.4 1859.27   206.2 1855.96  223.571855.706  231.341855.743   334.1  1855.8
     344 1857.51  353.571855.941   370.2 1850.53   373.5  1848.9   376.8 1848.63
   383.3  1849.6   386.1 1851.04  396.311855.689   406.3 1856.45   442.4 1855.75
   553.8 1856.46   599.8 1858.41   612.9 1859.87   694.9 1874.81   727.7  1878.7
#Mann= 10 ,-1 , 0
       0     .06       0  108.94     .12       0  155.78     .06       0
  160.71    .016       0  223.57     .08       0  231.34     .04       0
  353.57     .12       0   370.2    .045       0   386.1     .12       0
  396.31     .06       0
Bank Sta=370.2,386.1
XS Rating Curve= 0 ,0
Exp/Cntr=0.3,0.1

Type RM Length L Ch R = 1 ,8166.4  ,252.3,250,246.5
XS GIS Cut Line= 3
     2043862.656       151239.28     2044189.861      151398.758
     2044517.065      151558.236
#Sta/Elev= 30
       0 1876.37   27.151871.529   58.031864.391    78.7 1860.77    85.3 1861.73
   90.891860.087    98.4 1858.23  123.751857.932   134.4 1855.77  156.611855.735
   308.2 1855.83   321.4 1857.51  329.881856.276   350.9 1849.17   354.2 1847.96
   360.7 1847.28   367.3 1847.33   371.5 1849.33   373.8 1850.83   377.1 1851.86
   383.7  1852.7  405.571853.656   436.1 1853.36   511.6 1855.39     564  1858.6
   593.6 1861.75   636.2 1867.89   701.8 1875.96   711.6 1878.28     728 1880.09
#Mann= 10 ,-1 , 0
       0     .06       0   27.15     .08       0   58.03     .12       0
   90.89    .016       0  123.75     .08       0  156.61     .04       0
  329.88     .12       0   350.9    .045       0   371.5     .12       0
  405.57     .06       0
Bank Sta=350.9,371.5
XS Rating Curve= 0 ,0
Exp/Cntr=0.3,0.1

Type RM Length L Ch R = 1 ,7916.4  ,279.3,284.5,288.1
XS GIS Cut Line= 3
     2043750.347      151510.505     2044094.388      151629.142
     2044440.659      151742.801
#Sta/Elev= 30
       0 1868.33    29.5 1854.62   44.721851.334    52.5 1850.45    75.4 1850.46
   83.351849.804    91.8 1849.32   114.8 1849.41   137.7 1847.37   180.3 1847.13
   190.2 1847.65   278.7 1847.22   291.8 1848.35  319.891849.103   347.5  1849.8
   350.8 1848.76   356.4 1845.98   360.6 1844.65   367.2 1844.52   373.7 1845.56
     390 1848.67  395.361848.714   425.8 1848.84   484.3 1851.01   565.7 1856.28
   585.2 1859.03   643.8 1869.91   653.5 1872.37   689.3 1877.27   728.4 1881.21
#Mann= 7 ,-1 , 0
       0     .12       0   44.72    .016       0   83.35     .06       0
  319.89     .12       0   356.4    .045       0   373.7     .12       0
  395.36     .06       0
#XS Ineff= 2 , 0
           294.4 1856.98
Permanent Ineff=
       F       F
Bank Sta=356.4,373.7
XS Rating Curve= 0 ,0
Exp/Cntr=0.3,0.1

Type RM Length L Ch R = 1 ,7631.9  ,116.4,110.3,104
XS GIS Cut Line= 3
     2043602.805      151625.124     2043685.094      151710.067
     2044329.801      152067.832
#Sta/Elev= 30
       0 1888.86    44.8 1884.73    51.1 1883.06    99.1 1854.96   115.1 1849.35
   124.8 1847.87   167.4 1847.07   255.9 1847.97   285.4 1849.44   298.5 1859.06
   311.6 1860.14   331.3 1857.96   347.7  1848.1   357.5 1844.11   373.9 1842.93
   436.1 1843.39   495.1 1845.38   501.7 1844.47   506.8 1841.86   511.5 1841.01
   521.8 1842.24   527.9 1844.26   554.1  1845.3     577 1853.78   590.2 1856.94
     659 1866.45   668.8 1868.95   708.1 1873.25   783.5 1887.52   855.6 1895.32
#Mann= 12 ,-1 , 0
       0     .08       0    44.8     .12       0   124.8     .08       0
   167.4     .06       0   255.9     .12       0   311.6     .06       0
   357.5     .12       0   373.9     .06       0   436.1     .12       0
   506.8    .045       0   521.8     .12       0   590.2     .06       0
#XS Ineff= 2 , 0
          406.44 1856.93
Permanent Ineff=
       F       F
Bank Sta=506.8,521.8
XS Rating Curve= 0 ,0
Exp/Cntr=0.3,0.1

Type RM Length L Ch R = 1 ,7521.6  ,351.8,363.5,374.4
XS GIS Cut Line= 3
     2043615.826      151946.304     2043937.006      151991.877
     2044325.461      152089.533
#Sta/Elev= 30
       0 1847.53      59 1848.74   137.6 1848.32   176.9 1847.16   193.3 1846.48
   252.3  1845.9   268.7 1846.18   278.5 1845.83   317.8 1846.65   330.9 1846.03
   363.5 1845.56   379.8 1844.65   386.3 1844.75   389.5 1843.36     392 1841.63
     396 1840.33   405.8 1840.42   409.1 1841.57   412.3 1842.51   425.4    1843
   435.1 1844.52   461.2 1853.02   474.2 1858.16   500.2 1862.82   513.3 1865.14
   532.8 1867.61   571.9 1873.61   682.6 1891.43   708.7  1894.4   724.9 1895.32
#Mann= 6 ,-1 , 0
       0     .08       0   176.9    .016       0   363.5     .12       0
     392    .045       0   409.1     .12       0   500.2     .06       0
Bank Sta=392,409.1
XS Rating Curve= 0 ,0
Exp/Cntr=0.3,0.1

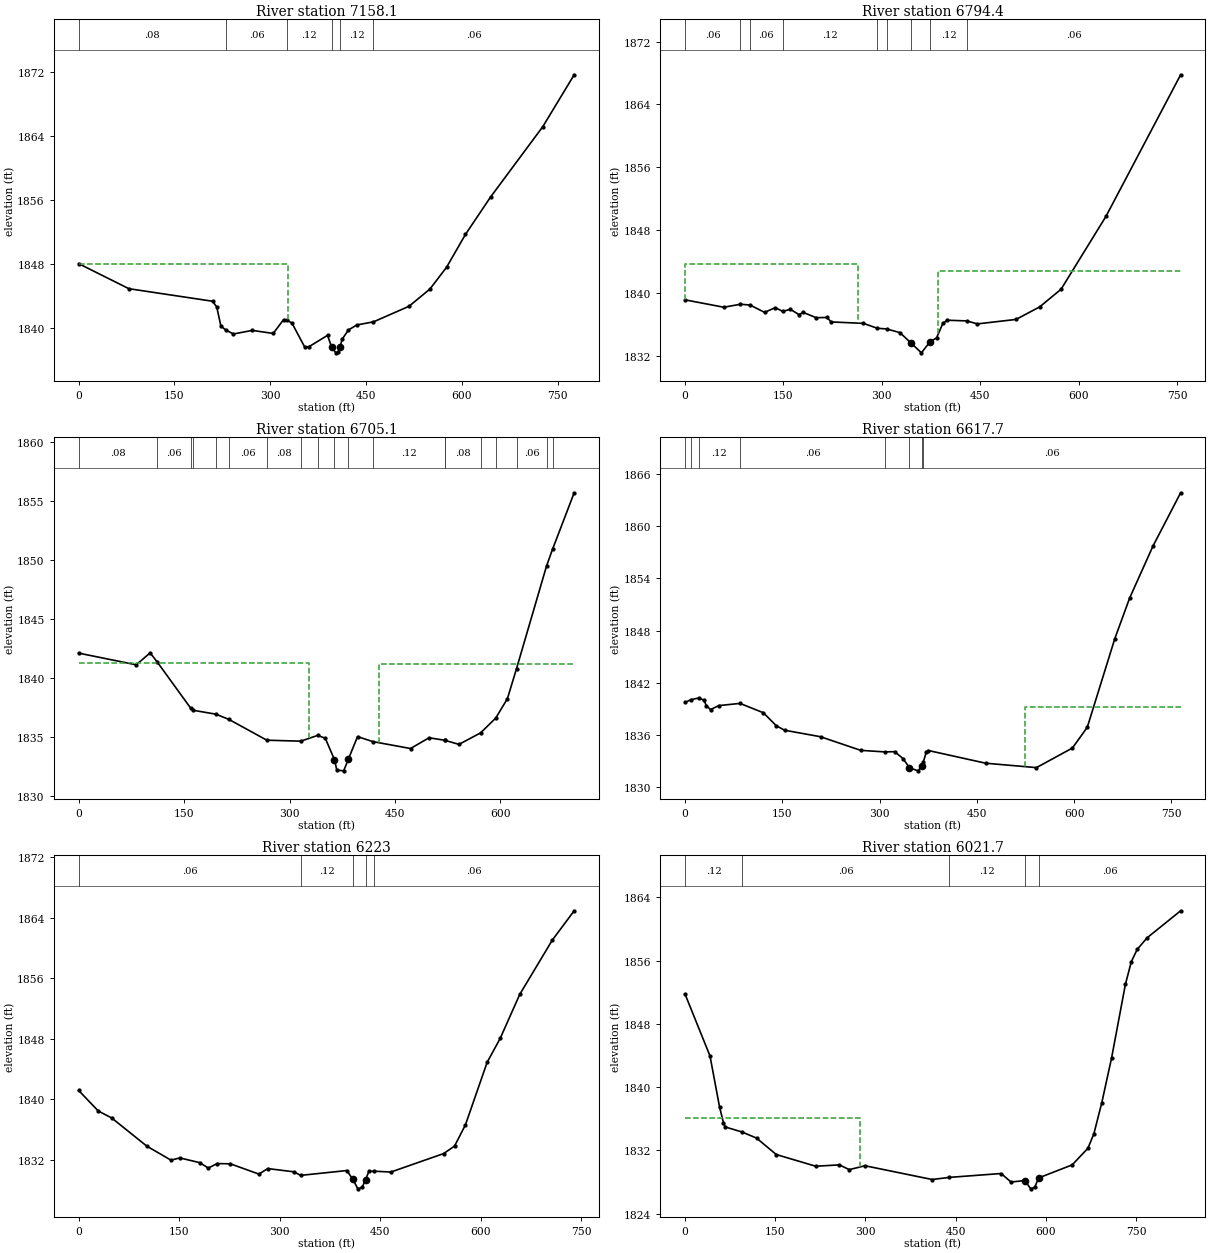
Type RM Length L Ch R = 1 ,7158.1  ,349.2,363.7,338.1
XS GIS Cut Line= 3
     2043619.526      152064.697     2043737.201      152136.256
     2044223.807      152549.311
#Sta/Elev= 30
       0 1848.04    78.7  1844.9   209.7 1843.33   216.3 1842.61   222.8 1840.21
  230.821839.708   242.5 1839.23   271.9 1839.68   304.7  1839.3     321 1841.03
  326.451840.954   334.1 1840.59   353.8 1837.63   360.3 1837.62   389.8 1839.06
   396.3 1837.56   402.9 1836.87   406.1 1836.92   409.4 1837.63   412.7 1838.58
   422.5 1839.73   435.6 1840.36  461.74 1840.75   517.4  1842.7   550.2 1844.86
   576.3  1847.6   605.8  1851.7   645.1 1856.38   726.9 1865.19     776 1871.68
#Mann= 6 ,-1 , 0
       0     .08       0  230.82     .06       0  326.45     .12       0
   396.3    .045       0   409.4     .12       0  461.74     .06       0
#XS Ineff= 2 , 0
          327.42 1848.05
Permanent Ineff=
       F       F
Bank Sta=396.3,409.4
XS Rating Curve= 0 ,0
Exp/Cntr=0.3,0.1

Type RM Length L Ch R = 1 ,6794.4  ,89.2,89.3,108.5
XS GIS Cut Line= 3
     2043479.588      152295.276     2043939.157      152621.267
     2044112.489      152703.958
#Sta/Elev= 30
       0 1839.15      59 1838.21   84.431838.591   98.951838.494   121.2 1837.56
   137.6 1838.16  148.731837.685   160.5 1837.94   173.6 1837.28   180.2 1837.55
   199.8 1836.88   216.2 1836.91   222.8 1836.34   271.9 1836.16  292.971835.536
  307.25 1835.45   327.6 1834.98     344 1833.69   360.3 1832.41   373.4 1833.82
   383.3  1834.3   393.1 1836.18   399.6 1836.56  429.74 1836.47   445.5 1836.09
   504.5 1836.66   540.5 1838.25   573.2  1840.5   641.6 1849.76   755.5 1867.78
#Mann= 9 ,-1 , 0
       0     .06       0   84.43     .08       0   98.95     .06       0
  148.73     .12       0  292.97     .08       0  307.25     .12       0
     344    .045       0   373.4     .12       0  429.74     .06       0
#XS Ineff= 2 , 0
          263.65 1843.76  386.21         1842.81
Permanent Ineff=
       F       F
Bank Sta=344,373.4
XS Rating Curve= 0 ,0
Exp/Cntr=0.3,0.1

Type RM Length L Ch R = 1 ,6705.1  ,88.4,87.4,86.8
XS GIS Cut Line= 2
     2043430.292      152368.425     2044005.945      152775.517
#Sta/Elev= 30
       0 1842.13      82 1841.14   101.7 1842.15  111.391841.416  159.221837.484
  162.551837.295   195.41836.957  213.721836.519  267.761834.755  316.051834.673
  340.111835.162   350.9 1834.92     364  1833.1   367.3 1832.22   377.1 1832.16
   383.7 1833.14   396.8 1835.06  418.371834.638   472.2 1834.05   498.5 1834.96
  520.651834.754     5211834.747   541.1  1834.4  571.871835.375  593.361836.624
     610 1838.27  623.031840.826  665.721849.513  674.191850.923     705 1855.71
#Mann= 19 ,-1 , 0
       0     .08       0  111.39     .06       0  159.22     .08       0
  162.55     .06       0   195.4     .08       0  213.72     .06       0
  267.76     .08       0  316.05     .06       0  340.11     .08       0
     364    .045       0   383.7     .08       0  418.37     .12       0
  520.65     .06       0     521     .08       0  571.87     .06       0
  593.36     .08       0  623.03     .06       0  665.72     .08       0
  674.19     .06       0
#XS Ineff= 2 , 0
          327.42 1841.32  426.91         1841.25
Permanent Ineff=
       F       F
Bank Sta=364,383.7
XS Rating Curve= 0 ,0
Exp/Cntr=0.3,0.1

Type RM Length L Ch R = 1 ,6617.7  ,393.1,394.6,363
XS GIS Cut Line= 3
     2043384.176      152449.525     2043875.549      152783.468
     2044039.339      152829.584
#Sta/Elev= 30
       0 1839.71    8.991840.028   20.85 1840.22    29.4 1839.97    32.6 1839.34
    39.2 1838.89    52.2 1839.35   84.751839.599   120.8 1838.52   140.4 1837.04
   153.4 1836.51   208.9 1835.76   270.9 1834.19  308.46 1834.01   323.2 1834.04
   336.2 1833.24     346 1832.19   359.1 1831.83   365.6 1832.39  367.531832.887
   372.1 1834.01   375.4 1834.17   463.5 1832.71   541.9  1832.2   597.4 1834.46
   620.3 1836.85   662.8 1847.07   685.7 1851.75   721.7 1857.74   764.3 1863.87
#Mann= 8 ,-1 , 0
       0     .12       0    8.99     .06       0   20.85     .12       0
   84.75     .06       0  308.46     .12       0     346    .045       0
   365.6     .12       0  367.53     .06       0
#XS Ineff= 2 , 0
                          523.69         1839.17
Permanent Ineff=
       F       F
Bank Sta=346,365.6
XS Rating Curve= 0 ,0
Exp/Cntr=0.3,0.1

Type RM Length L Ch R = 1 ,6223    ,205.5,201.4,198.2
XS GIS Cut Line= 3
     2043347.602      153029.949     2043869.188      152832.764
     2044048.881      152859.798
#Sta/Elev= 30
       0 1841.15    29.5 1838.42    49.2 1837.52   101.7 1833.79   137.8 1831.93
   150.9 1832.23   180.4 1831.61   193.5 1830.89   206.6 1831.48   226.3 1831.45
     269 1830.09   282.1 1830.82   321.4 1830.39  331.07 1829.92   400.2 1830.56
     409 1829.41   416.6 1828.14   423.1 1828.34  428.01 1829.35     433 1830.44
  440.371830.476   465.8 1830.36   544.5  1832.8   560.9  1833.8   577.1 1836.61
   609.5 1844.88     629 1848.05   658.2 1853.87   706.9 1861.06   739.3 1864.91
#Mann= 5 ,-1 , 0
       0     .06       0  331.07     .12       0     409    .045       0
  428.01     .12       0  440.37     .06       0
Bank Sta=409,428.01
XS Rating Curve= 0 ,0
Exp/Cntr=0.3,0.1

Type RM Length L Ch R = 1 ,6021.7  ,156.8,161.3,154.7
XS GIS Cut Line= 3
     2043318.978      153222.363     2043408.029      153228.724
     2044072.734      152915.455
#Sta/Elev= 30
       0 1851.73    41.4 1843.93    57.4 1837.43    63.8 1835.48      67 1834.94
   94.491834.314   118.8 1833.54   151.6 1831.46   217.2 1829.98   256.6 1830.15
     273 1829.55   299.2 1830.04   410.8  1828.3  439.331828.567   525.6 1829.06
     542 1827.98     565 1828.17   574.8 1827.12   581.4 1827.31   587.9  1828.5
   643.7 1830.15   669.9 1832.25   679.8 1834.08   692.9 1837.99   709.3 1843.69
   732.2 1852.97   742.1 1855.86   751.9 1857.41   768.3 1858.87   824.1 1862.29
#Mann= 5 ,-1 , 0
       0     .12       0   94.49     .06       0  439.33     .12       0
     565    .045       0   587.9     .06       0
#XS Ineff= 2 , 0
          291.69 1836.14
Permanent Ineff=
       F       F
Bank Sta=565,587.9
XS Rating Curve= 0 ,0
Exp/Cntr=0.3,0.1

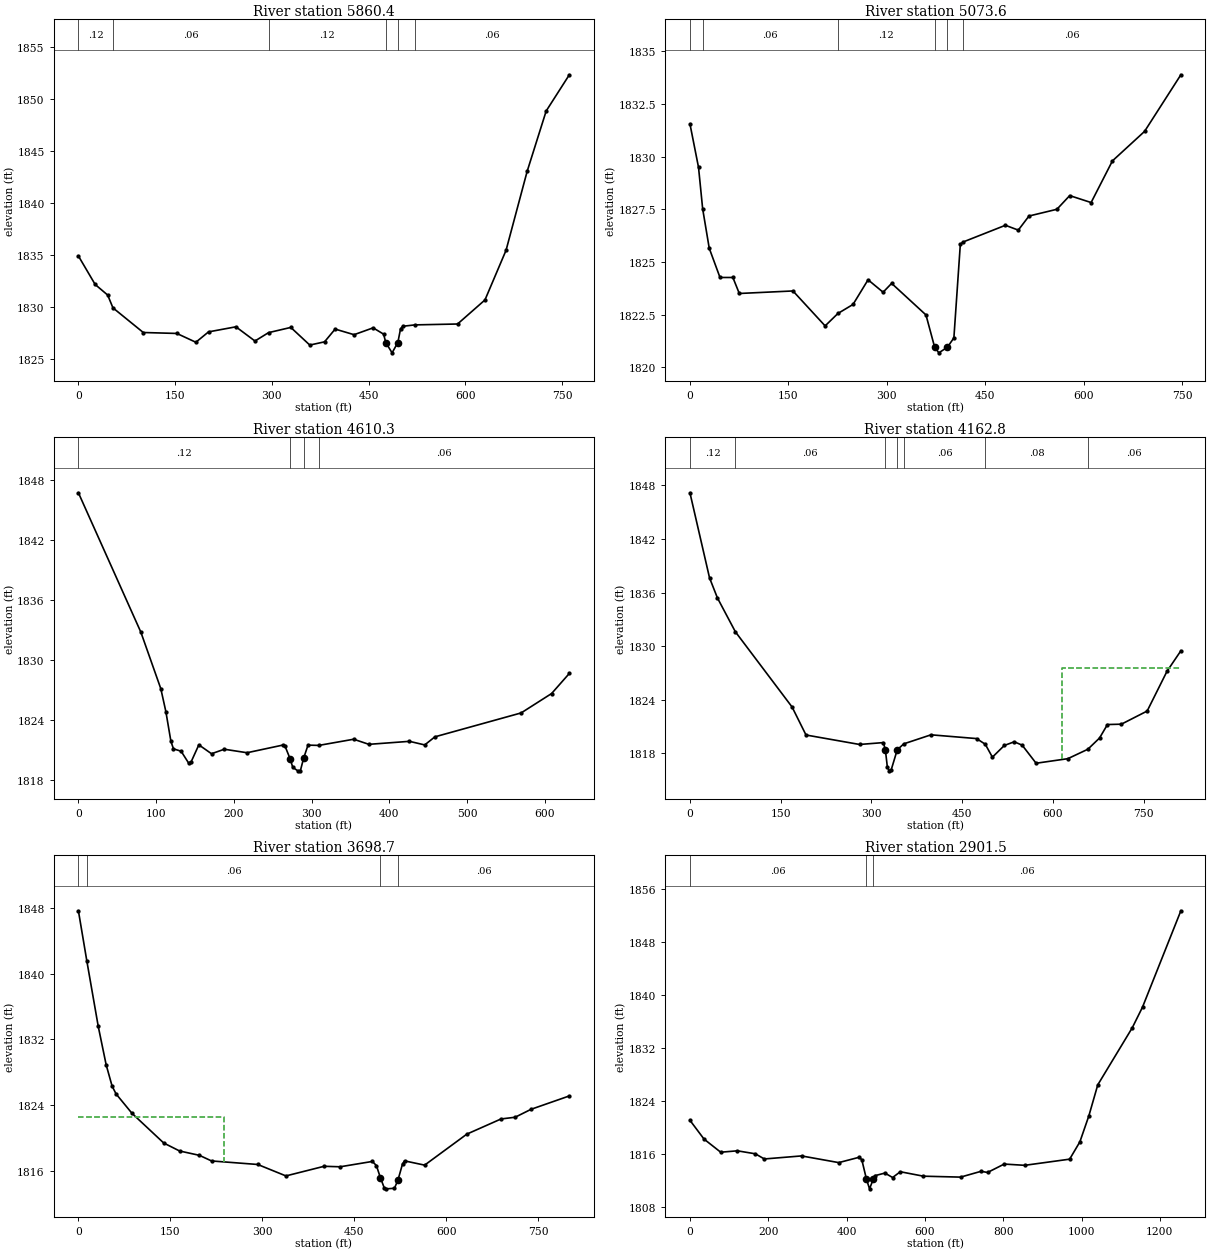
Type RM Length L Ch R = 1 ,5860.4  ,811.9,786.8,791.5
XS GIS Cut Line= 3
     2043455.735      153397.286     2043597.263       153349.58
     2044101.357      153002.916
#Sta/Elev= 30
       0 1834.89      26 1832.14    45.4 1831.12   53.551829.887   100.6 1827.51
   152.6 1827.42   182.1 1826.57   201.7 1827.57   244.2 1828.06   273.7 1826.69
  294.761827.497   329.3    1828   358.7  1826.3   381.6 1826.61     398 1827.84
   427.4  1827.3   456.9 1827.96   473.2 1827.35   476.5 1826.54   486.3 1825.55
   495.2 1826.54   499.4 1827.86   502.7 1828.11  521.731828.245   587.8 1828.33
   630.3 1830.65     663 1835.44   695.7 1843.05   725.2 1848.87   761.1 1852.36
#Mann= 6 ,-1 , 0
       0     .12       0   53.55     .06       0  294.76     .12       0
   476.5    .045       0   495.2     .12       0  521.73     .06       0
Bank Sta=476.5,495.2
XS Rating Curve= 0 ,0
Exp/Cntr=0.3,0.1

Type RM Length L Ch R = 1 ,5073.6  ,389.6,463.3,458.3
XS GIS Cut Line= 3
      2043573.41      153608.782     2044128.391      153581.749
     2044301.723       153664.44
#Sta/Elev= 30
       0 1831.56    13.1 1829.49   19.391827.522    29.4 1825.65    45.8 1824.26
    65.4 1824.26    75.2  1823.5   156.9 1823.62   205.9 1821.96  225.38 1822.55
   248.4 1822.98   271.3 1824.15   294.2 1823.56   307.2 1823.98   359.5 1822.48
   372.6 1820.96   379.1 1820.68   392.2 1820.95     402 1821.39   411.8 1825.83
  415.941825.945   480.5 1826.74   500.1 1826.51   516.4 1827.18   558.9  1827.5
   578.4 1828.15     611 1827.82   643.5  1829.8   692.4  1831.2   747.7 1833.89
#Mann= 6 ,-1 , 0
       0     .12       0   19.39     .06       0  225.38     .12       0
   372.6    .045       0   392.2     .12       0  415.94     .06       0
Bank Sta=372.6,392.2
XS Rating Curve= 0 ,0
Exp/Cntr=0.3,0.1

Type RM Length L Ch R = 1 ,4610.3  ,432.3,447.6,451.6
XS GIS Cut Line= 3
     2043540.016      153798.016     2043635.428      153844.132
     2044153.834      153930.003
#Sta/Elev= 30
       0 1846.75    80.3 1832.82     106 1827.16   112.5 1824.87     119 1821.89
   122.3 1821.15   132.1 1820.91   141.9 1819.71   145.1 1819.87   154.9 1821.55
   171.2 1820.66   187.6 1821.11   216.9 1820.76   262.6 1821.52   265.9 1821.39
   272.4 1820.13   275.7  1819.3   282.2 1818.95   285.5 1818.96   289.6  1820.2
   295.3 1821.52  309.191821.493     354 1822.11   373.6  1821.6   425.8  1821.9
   445.4 1821.54   458.5 1822.35   569.4 1824.74   608.6 1826.68   631.4 1828.69
#Mann= 4 ,-1 , 0
       0     .12       0   272.4    .045       0   289.6     .12       0
  309.19     .06       0
Bank Sta=272.4,289.6
XS Rating Curve= 0 ,0
Exp/Cntr=0.3,0.1

Type RM Length L Ch R = 1 ,4162.8  ,460.7,464,445.5
XS GIS Cut Line= 3
     2043404.849      153858.444     2043482.769       153985.66
     2044031.388      154356.177
#Sta/Elev= 30
       0 1847.16    32.4 1837.64    45.4  1835.4   75.111831.606   168.8 1823.19
   191.8 1820.06   280.3    1819   319.6 1819.21   322.9 1818.41   326.2 1816.48
   329.4 1816.05   332.7 1816.19   342.6 1818.41  353.421819.071   398.3 1820.08
   473.6 1819.66  487.981819.027   499.8 1817.58   519.5 1818.89   535.9  1819.3
     549 1818.92     572  1816.9   624.4 1817.41  657.461818.464   676.8 1819.72
   689.9 1821.23   712.9 1821.27   755.5 1822.74   788.3 1827.19   811.2 1829.48
#Mann= 7 ,-1 , 0
       0     .12       0   75.11     .06       0   322.9    .045       0
   342.6     .12       0  353.42     .06       0  487.98     .08       0
  657.46     .06       0
#XS Ineff= 2 , 0
                          615.04         1827.58
Permanent Ineff=
       F       F
Bank Sta=322.9,342.6
XS Rating Curve= 0 ,0
Exp/Cntr=0.3,0.1

Type RM Length L Ch R = 1 ,3698.7  ,707.9,797.2,576.2
XS GIS Cut Line= 3
     2043225.318      154066.901     2043280.813      154249.634
     2043794.448      154578.805
#Sta/Elev= 30
       0 1847.63   13.69 1841.56    32.4 1833.57    45.3 1828.91      55 1826.32
    61.5 1825.37    87.4 1823.02   139.2 1819.41   165.1 1818.44   197.5 1817.91
   217.2 1817.23   292.6  1816.8   338.6 1815.41   400.9 1816.58   427.1 1816.52
   479.6 1817.17   486.2 1816.67   492.7  1815.2   499.3  1813.9   502.6 1813.84
   515.7 1813.91   521.6 1814.96   528.8 1816.86   532.1 1817.24   564.9 1816.72
   633.8 1820.49   689.5 1822.33   712.5 1822.54   738.7 1823.51     801 1825.13
#Mann= 4 ,-1 , 0
       0     .12       0   13.69     .06       0   492.7    .045       0
   521.6     .06       0
#XS Ineff= 2 , 0
          237.42 1822.57
Permanent Ineff=
       F       F
Bank Sta=492.7,521.6
XS Rating Curve= 0 ,0
Exp/Cntr=0.3,0.1

Type RM Length L Ch R = 1 ,2901.5  ,402.6,414.5,404.7
XS GIS Cut Line= 3
     2042818.487      154265.331     2043520.934      154952.503
     2043773.348      155050.922
#Sta/Elev= 30
       0 1821.06      36 1818.22    78.6 1816.24   121.2 1816.45     167    1816
     190 1815.22     285 1815.68     380 1814.67   432.4 1815.48   438.9  1815.1
  450.69 1812.18   458.6 1810.71   468.4  1812.2   471.7 1812.69   497.9 1813.09
   517.5 1812.42   537.2 1813.29   596.2 1812.62   691.1 1812.48   743.6 1813.36
   759.9 1813.18   802.5 1814.45   854.9 1814.26   969.6 1815.19   995.7  1817.8
  1018.6 1821.72  1041.4 1826.41  1129.6 1835.04  1155.7 1838.15  1253.6 1852.69
#Mann= 3 ,-1 , 0
       0     .06       0  450.69    .045       0   468.4     .06       0
Bank Sta=450.69,468.4
XS Rating Curve= 0 ,0
Exp/Cntr=0.3,0.1