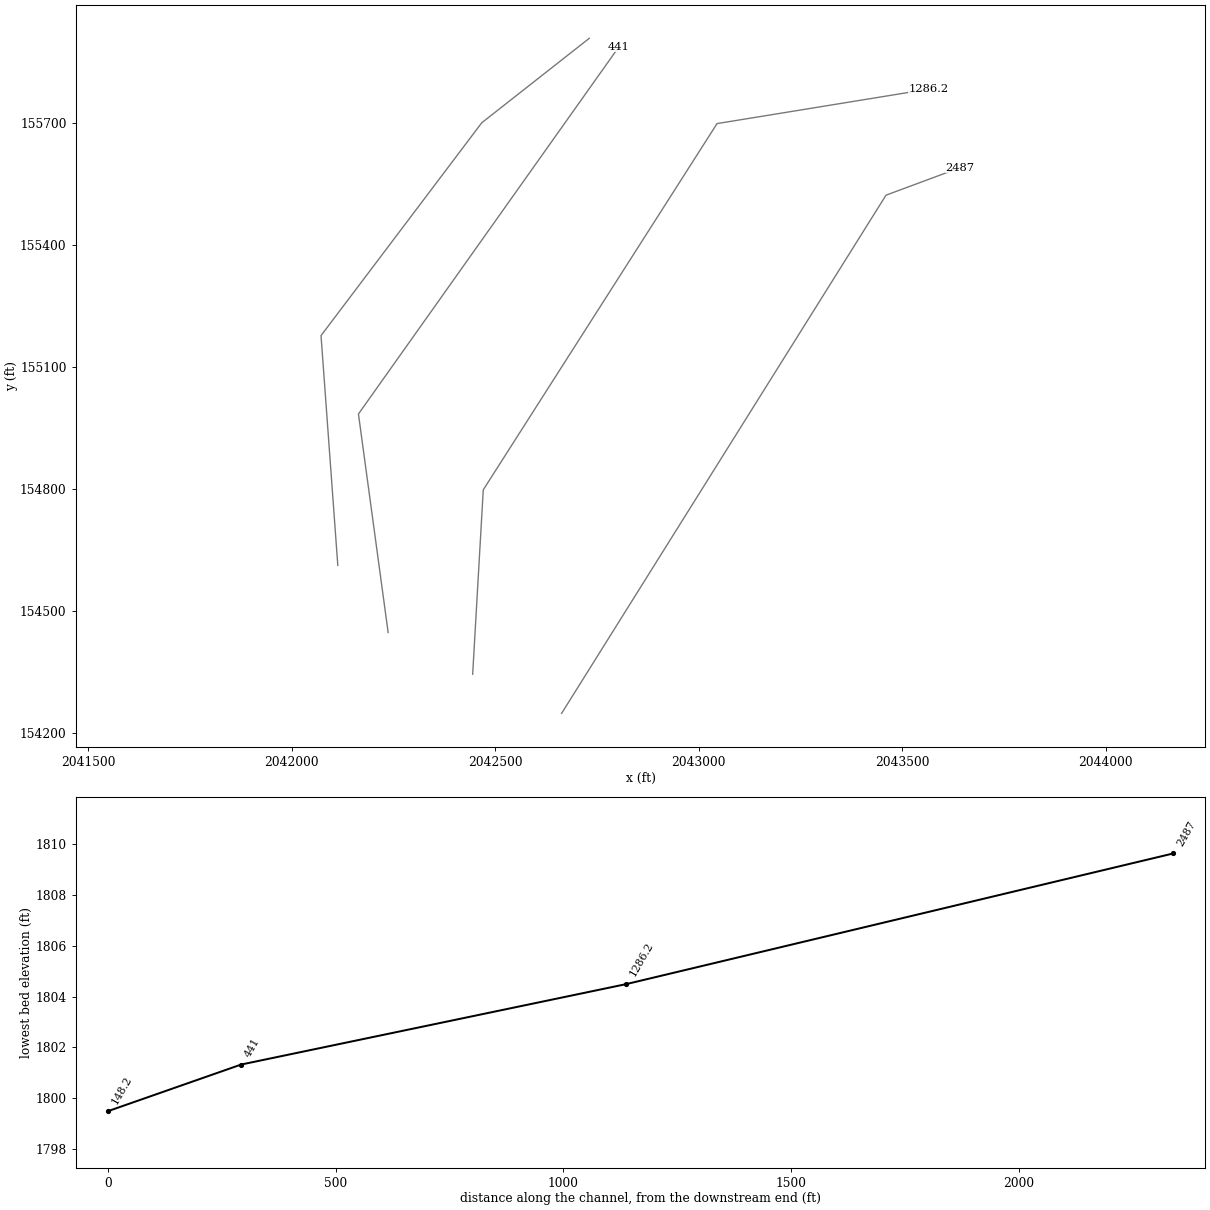
HEC-RAS study CRCKDCK.prj: CRCKDCK

--- CRCKDCK.g01 (geometry) --- (continued)

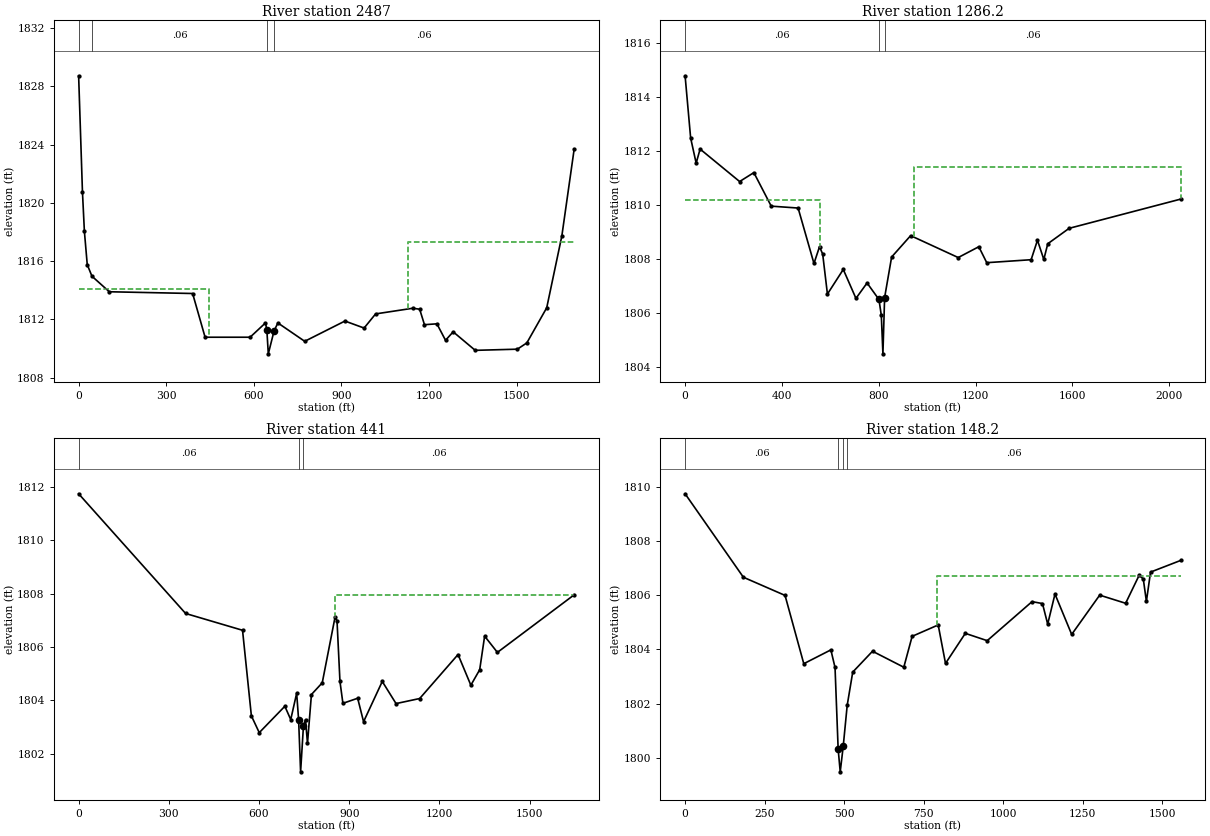
Type RM Length L Ch R = 1 ,2487    ,1091.7,1200.8,960.5
XS GIS Cut Line= 3
     2042662.888      154248.983      2043459.98      155522.276
     2043642.272      155589.984
#Sta/Elev= 30
       0 1828.72    13.1 1820.75    19.7 1818.05    29.5 1815.76   45.641814.965
     105  1813.9   390.3 1813.78     433 1810.78   587.1 1810.78   639.6 1811.76
   644.4  1811.3   649.4 1809.64   669.1 1811.21   682.2 1811.76   774.1  1810.5
   911.8 1811.89   977.4 1811.41  1016.8 1812.38  1144.7 1812.77  1167.7  1812.7
  1184.1 1811.64  1226.7  1811.7  1256.2 1810.57  1282.4 1811.15  1357.9 1809.88
  1502.2 1809.96  1534.6 1810.39  1602.7  1812.8  1654.5 1817.73  1696.7 1823.69
#Mann= 4 ,-1 , 0
       0     .12       0   45.64     .06       0   644.4    .045       0
   669.1     .06       0
#XS Ineff= 2 , 0
          446.69 1814.08 1128.43         1817.32
Permanent Ineff=
       F       F
Bank Sta=644.4,669.1
XS Rating Curve= 0 ,0
Exp/Cntr=0.3,0.1

Type RM Length L Ch R = 1 ,1286.2  ,792.4,845.2,772.7
XS GIS Cut Line= 4
     2042444.355      154345.192     2042470.397      154798.317
     2043044.833      155698.202     2043564.147      155782.692
#Sta/Elev= 30
       0 1814.77    22.9 1812.47    45.7 1811.54      62 1812.06   225.3 1810.86
   284.1 1811.19   355.9 1809.95     467 1809.88   532.5 1807.83   555.4 1808.45
   568.5 1808.18   588.1  1806.7   653.6 1807.61     706 1806.54   751.9 1807.11
     801  1806.5   810.8 1805.91   817.4 1804.49   824.4 1806.57   853.4 1808.07
     932 1808.86  1128.5 1808.05  1213.6 1808.45  1246.4 1807.86  1429.8 1807.97
    1456 1808.69  1482.2 1807.98  1498.6 1808.56  1586.8 1809.13  2047.6 1810.21
#Mann= 3 ,-1 , 0
       0     .06       0     801    .045       0   824.4     .06       0
#XS Ineff= 2 , 0
          558.22 1810.16  946.86          1811.4
Permanent Ineff=
       F       F
Bank Sta=801,824.4
XS Rating Curve= 0 ,0
Exp/Cntr=0.3,0.1

Type RM Length L Ch R = 1 ,441     ,230.4,292.8,322.2
XS GIS Cut Line= 3
     2042236.673      154447.768     2042163.694      154984.628
      2042803.73      155886.859
#Sta/Elev= 30
       0 1811.75   355.8 1807.26   545.1 1806.63   574.5 1803.42   600.7 1802.79
   685.8 1803.78   705.4 1803.28   725.1 1804.27   731.6 1803.27   738.2 1801.32
   747.7 1803.05   754.5 1803.28   761.1 1802.39   774.2 1804.22   810.2 1804.66
   852.7 1807.12   859.3 1806.99   869.1 1804.71   878.9 1803.89     928 1804.08
   947.6  1803.2  1009.8 1804.71  1055.6 1803.88  1134.2 1804.07  1261.8 1805.72
  1304.4 1804.57  1333.8 1805.15  1350.2 1806.41  1392.7  1805.8    1648 1807.96
#Mann= 3 ,-1 , 0
       0     .06       0   731.6    .045       0   747.7     .06       0
#XS Ineff= 2 , 0
                           853.7         1807.94
Permanent Ineff=
       F       F
Bank Sta=731.6,747.7
XS Rating Curve= 0 ,0
Exp/Cntr=0.3,0.1

Type RM Length L Ch R = 1 ,148.2   ,163.4,148.2,132.5
XS GIS Cut Line= 4
     2042112.975      154612.698     2042071.742      155177.224
     2042466.708      155700.227     2042730.814      155907.692
#Sta/Elev= 30
       0 1809.74   183.2 1806.66   314.1 1805.99     373 1803.47   458.1 1803.98
   471.2 1803.33     481 1800.32   487.5 1799.48   496.9 1800.42  509.431801.935
   526.8 1803.16     589 1803.93   687.3 1803.34   713.5 1804.48   795.4  1804.9
   818.4 1803.48   880.6 1804.59   949.4 1804.32  1090.3 1805.76  1123.1 1805.69
  1139.5 1804.93  1162.4 1806.04  1214.9 1804.55  1302.9    1806  1384.4  1805.7
  1426.8 1806.73  1439.9  1806.6  1449.7 1805.77  1462.7 1806.85  1557.3 1807.28
#Mann= 4 ,-1 , 0
       0     .06       0     481    .045       0   496.9     .12       0
  509.43     .06       0
#XS Ineff= 2 , 0
                           790.5          1806.7
Permanent Ineff=
       F       F
Bank Sta=481,496.9
XS Rating Curve= 0 ,0
Exp/Cntr=0.3,0.1

Chan Stop Cuts=-1
Use User Specified Reach Order=0
Composite Channel Slope=5